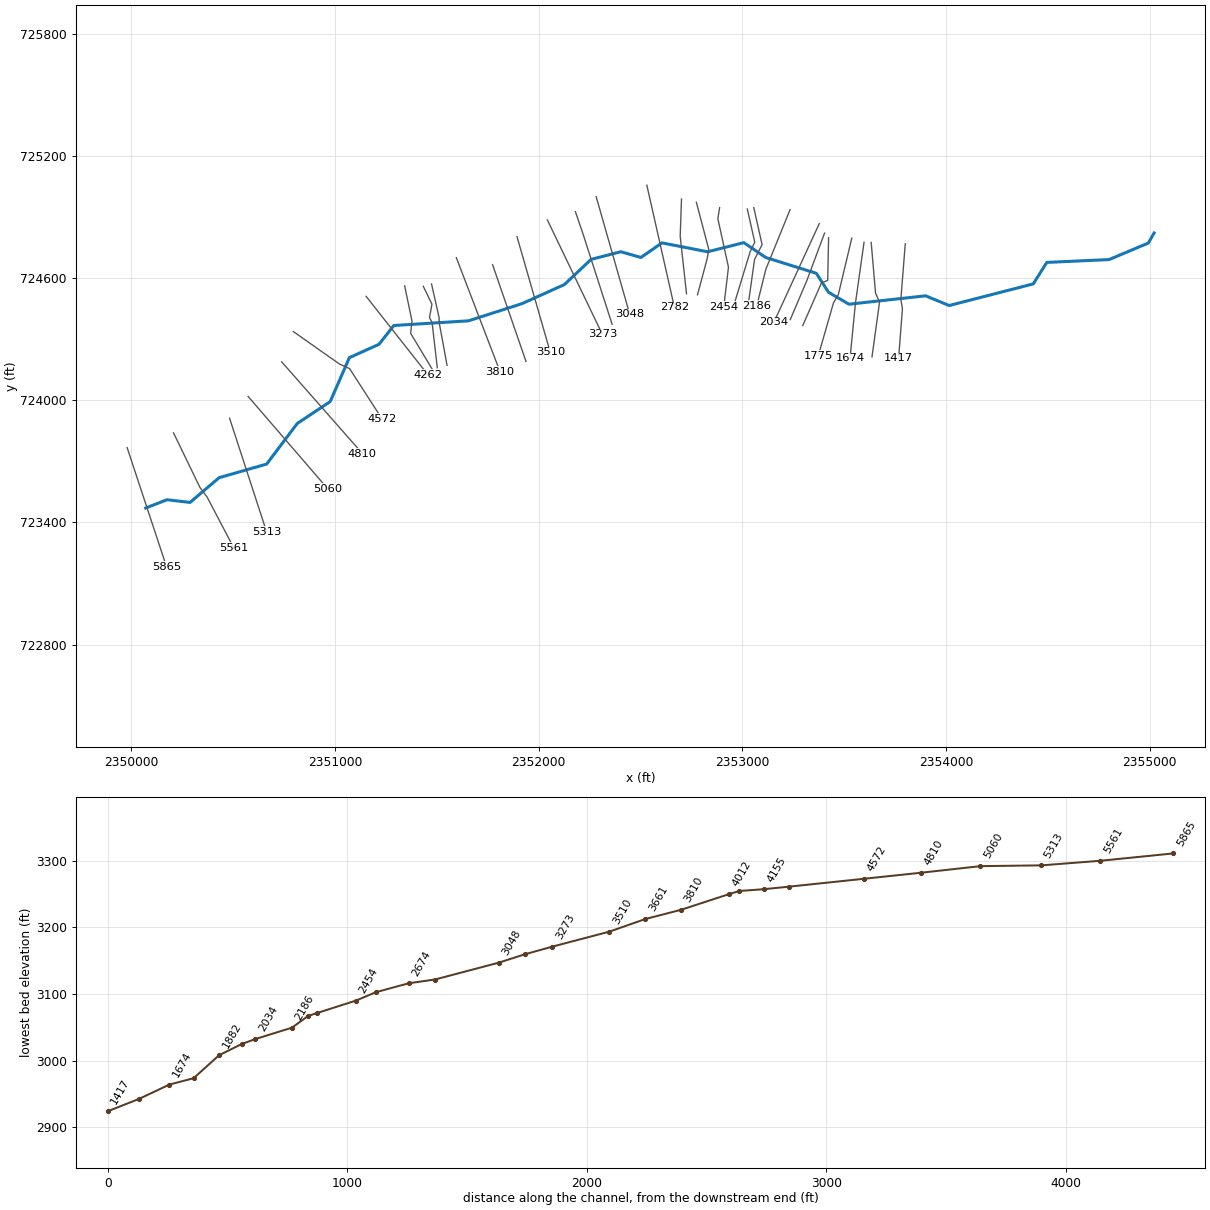
--- OTTERCKT1.prj (project) ---

Proj Title=OTTERCKT1
Current Plan=p01
Default Exp/Contr=0,0
English Units
Geom File=g01
Flow File=f01
Plan File=p01
BEGIN DESCRIPTION:
----------MODEL BY WOOD PLC 2022----------
AFH study
Randolph County, WV
HEC-RAS Version: RAS 6.2
Vertical Datum: NAVD88
Projection: NAD 1983 StatePlane West Virginia S FIPS 4702 (US Feet)
Terrain: 1-meter LIDAR (FEMA Region III 3DEP collected 2016-2018)
Land Use: 2019 NLCD
Hydrologic Method:
WV SIR2010-5033 regression equations
Additional Model Notes:
None
END DESCRIPTION:
DSS Export Rating Curves= 0
DSS Export Rating Curve Sorted= 0
DSS Export Volume Flow Curves= 0
DXF OffsetX= 0
DXF OffsetY= 0
DXF ScaleX= 0
DXF ScaleY= 0

--- OTTERCKT1.p01 (plan) ---

Plan Title=Floodplain
Program Version=6.20
Short Identifier=Floodplain
Geom File=g01
Flow File=f01
Subcritical Flow
K Sum by GR= 0
Std Step Tol= 0.01
Critical Tol= 0.01
Num of Std Step Trials= 20
Max Error Tol= 0.3
Flow Tol Ratio= 0.001
Split Flow NTrial= 30
Split Flow Tol= 0.02
Split Flow Ratio= 0.02
Log Output Level= 0
Friction Slope Method= 1
Unsteady Friction Slope Method= 2
Unsteady Bridges Friction Slope Method= 1
Parabolic Critical Depth
Global Vel Dist= 0 , 0 , 0
Global Log Level= 0
CheckData=True
Encroach Param=-1 ,0,0, 0
Mapping Interval=1HOUR
Computation Time Step Use Courant=        0
Computation Time Step Use Time Series=    0
Computation Time Step Count To Double=0
Computation Time Step Max Doubling=0
Computation Time Step Max Halving=0
Computation Time Step Residence Courant=0
Run HTab= 0
Run UNet= 0
Run Sediment= 0
Run PostProcess= 0
Run WQNet= 0
Run RASMapper=-1
UNET Theta= 0
UNET Theta Warmup= 0
UNET ZTol= 0
UNET ZSATol= 0
UNET MxIter= 0
UNET Max Iter WO Improvement= 0
UNET MaxInSteps= 0
UNET DtIC= 0
UNET DtMin= 0
UNET MaxCRTS= 0
UNET WFStab= 0
UNET SFStab= 0
UNET WFX= 1
UNET SFX= 1
UNET Gravity=32.174
UNET 1D Methodology=Finite Difference
UNET DSS MLevel= 1
UNET Pardiso=0
UNET DZMax Abort= 0
UNET Use Existing IB Tables= 0
UNET Froude Reduction=False
UNET Froude Limit= 0
UNET Froude Power= 0
UNET D1 Cores= 0
UNET WindReference=Eulerian
UNET WindDragFormulation=Hsu (1988)
UNET D2 Coriolis=0
UNET D2 Cores= 0
UNET D2 Theta= 1
UNET D2 Theta Warmup= 1
UNET D2 Z Tol= 0.01
UNET D2 Volume Tol= 0.01
UNET D2 Max Iterations= 20
UNET D2 Equation= 0
UNET D2 RampUpFraction=0.1
UNET D2 TimeSlices= 1
UNET D2 Turbulence Formulation=Non-Conservative (original)
UNET D2 Eddy Viscosity=0.3
UNET D2 Transverse Eddy Viscosity=0.1
UNET D2 Smagorinsky Mixing=0
UNET D2 BCVolumeCheck=0
UNET D2 Cores=0
UNET D2 SolverType=PARDISO (Direct)
UNET D2 Minimum Iterations= 2147483647
UNET D2 Maximum Iterations= 2147483647
UNET D2 Restart Number= 10
UNET D2 Relaxation Coeff=1.3
UNET D2 SOR Precondition Iterations= 10
UNET D2 ILUT Maximum Fill= 8
UNET D2 ILUT Tolerance=1E-08
UNET D1D2 MaxIter= 0
UNET D1D2 ZTol=0.01
UNET D1D2 QTol=0.1
UNET D1D2 MinQTol=1
Write IC File= 0
Write IC File at Fixed DateTime=0
Write IC File at Sim End=0
Echo Input=False
Echo Parameters=False
Echo Output=False
Write Detailed= 0
HDF Write Warmup=0
HDF Write Time Slices=0
HDF Flush=0
HDF Compression= 1
HDF Chunk Size= 1
HDF Spatial Parts= 1
HDF Use Max Rows=0
HDF Fixed Rows= 1
Calibration Method= 0
Calibration Iterations= 20
Calibration Max Change=0.05
Calibration Tolerance=0.2
Calibration Maximum=1.5
Calibration Minimum=0.5
Calibration Optimization Method= 1
WQ AD Non Conservative
WQ ULTIMATE=-1
WQ Max Comp Step=1HOUR
WQ Output Interval=15MIN
WQ Output Selected Increments= 0
WQ Output face flow=0
WQ Output face velocity=0
WQ Output face area=0
WQ Output face dispersion=0
WQ Output cell volume=0
WQ Output cell surface area=0
WQ Output cell continuity=0
WQ Output cumulative cell continuity=0
WQ Output face conc=0
WQ Output face dconc_dx=0
WQ Output face courant=0
WQ Output face peclet=0
WQ Output face adv mass=0
WQ Output face disp mass=0
WQ Output cell mass=0
WQ Output cell source sink temp=0
WQ Output nsm pathways=0
WQ Output nsm derived pathways=0
WQ Create Restart=0
WQ Fixed Restart=0
WQ System Summary=0
WQ Write To DSS=0
Sorting and Armoring Iterations= 10
XS Update Threshold= 0.02
Bed Roughness Predictor= 0
Hydraulics Update Threshold= 0.02
Energy Slope Method= 1
Volume Change Method= 1
Sediment Retention Method= 0
Sediment TS Multiplier= 1
Warm Up Method= 0
XS Weighting Method= 0
Number of US Weighted Cross Sections= 1
Number of DS Weighted Cross Sections= 1
Upstream XS Weight=0
Main XS Weight=1
Downstream XS Weight=0
Number of DS XS's Weighted with US Boundary= 1
Upstream Boundary Weight= 1
Weight of XSs Associated with US Boundary= 0
Number of US XS's Weighted with DS Boundary= 1
Downstream Boundary Weight= 0.5
Weight of XSs Associated with DS Boundary= 0.5
Percentile Method= 0
Sediment Output Level= 3
Mass or Volume Output= 0
Output Increment Type= 1
Profile and TS Output Increment= 1
Transport Output Increment 1
XS Output Flag= 0
XS Output Increment= 10
Read HDF5 Sediment Hotstart= 0
Sediment Hotstart Type= 0
Write Gradation File= 0
Read Gradation Hotstart= 0
Write HDF5 File= 1
Write Binary Output= 1
Write DSS Sediment File= 0
DSS Sediment Output Type= 1
SV Curve= 0
Specific Gage Flag= 0
Subcell Erosion Methods= 0
Subcell Deposition Methods= 0
Advection Scheme= 1
Matrix Solver= 0
Implicit Weighting Factor= 1
Maximum Outer Loop Convergence Iterations= 5
Convergence Maximum Absolute= 0.001
Convergence RMSE= 0.0001
Grain Fractions Max Abs Error= 0.001
Max Subgrid Regions= 1
Max Subgrid Length Scale= 3.402823E+38
Initial Layer Thickness= 3.402823E+38
Min Layer Thickness= 3.402823E+38
Max Layer Thickness= 3.402823E+38
Number of Layers= 5

--- OTTERCKT1.f01 (steady flow) ---

Flow Title=Flow
Program Version=6.20
Number of Profiles= 1
Profile Names=P100yr
River Rch & RM=OTTERCKT1,Main,5865
     453
River Rch & RM=OTTERCKT1,Main,2674
     508
Boundary for River Rch & Prof#=OTTERCKT1,Main            , 1
Up Type= 0
Dn Type= 3
Dn Slope=0.05517
DSS Import GetInterval= 0
DSS Import GetPeak= 0
DSS Import FillOption= 0

--- OTTERCKT1.g01 (geometry) ---

Geom Title=Geometry
Program Version=6.20

River Reach=OTTERCKT1       ,Main
Reach XY= 30
2350069.70494314723470.4108439532350173.84678881723511.346658751
2350287.59400001723498.112000003     2350430.376723619.572000012
2350663.89599998723686.4800000342350814.06900002723885.699000016
2350975.96200001      723993.3382351070.29300004724209.196999997
2351215.84600003724274.8460000012351288.46200001724367.036000013
2351655.21500002724390.039000019     2351917.368724474.239999995
2352125.97500001724567.9270000162352257.62700002724691.974999994
2352403.41199999724729.2830000222352502.00300002724701.237000003
2352605.80499999724772.851000011     2352829.596724729.122999996
2353007.73830262724774.0092643452353114.85000001724701.237000003
2353363.57600003724623.3560000212353423.21192106724530.462078967
     2353523.705724471.6360000072353900.44100001724512.869000003
2354015.89199999724465.126000002     2354429.087724571.463000014
2354495.49300002724676.9309999942354801.04900001724690.819999993
2354994.19100001724771.982999995     2355022.347      724821.467

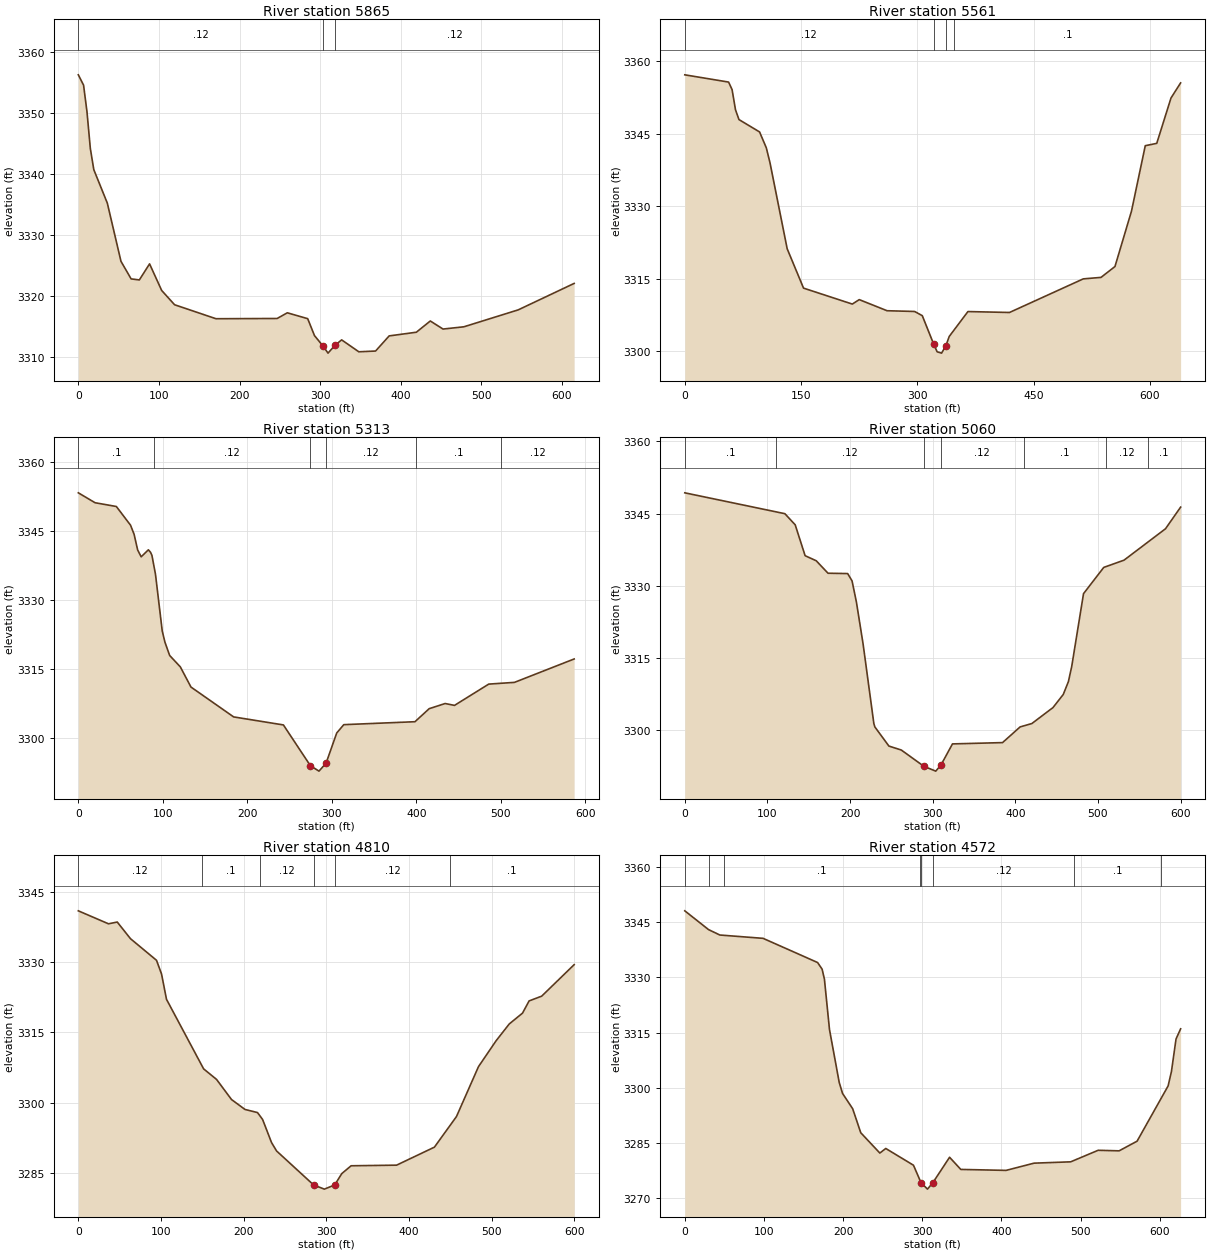
Type RM Length L Ch R = 1 ,5865    ,302.5,304.7,307.2
XS GIS Cut Line= 2
 2349978.7048915723767.3657561132350171.80834367723183.287413146
#Sta/Elev= 30
       0 3356.19     6.5  3354.5    10.7 3350.18    14.9 3344.13    19.2 3340.67
      36 3335.18    52.9 3325.67    65.5 3322.79    75.7 3322.62    88.4 3325.25
   103.4  3320.9   119.4 3318.56   170.8 3316.27   246.7 3316.31   259.3 3317.24
   284.6 3316.28     293 3313.51   303.7 3311.79   309.8 3310.64   318.3  3311.9
   326.7 3312.81     348 3310.86   368.8 3310.98   385.7 3313.46   419.4 3314.06
   436.7  3315.9   452.5 3314.58   478.4 3314.95   545.8 3317.72   615.2 3322.05
#Mann= 3 ,-1,0
       0     .12       0   303.7    .045       0   318.3     .12       0
Bank Sta=303.7,318.3
XS Rating Curve= 0 ,0
Exp/Cntr(USF)=0,0
Exp/Cntr=0.3,0.1

Type RM Length L Ch R = 1 ,5561    ,248.9,247.2,243.7
XS GIS Cut Line= 4
 2350206.3762456 723840.077549832350335.88259883723572.426450219
2350371.29815253723524.7409408982350502.84887445723274.169536426
#Sta/Elev= 30
       0 3357.17    56.5 3355.67      61 3354.12    65.4 3349.94    69.9 3347.91
    96.5 3345.35   105.2 3342.05   109.9 3338.99   132.1 3321.18   153.2 3313.04
   216.1 3309.74   225.1 3310.66     261 3308.36   296.5 3308.21   306.4 3307.34
   321.23301.412   325.6 3299.86   331.3 3299.59   336.83301.112   341.2 3303.05
   365.3 3308.19   418.9    3308   514.1 3314.95     537 3315.26     555 3317.51
   576.3 3328.96   594.1 3342.51   608.9 3342.99   627.3 3352.38   639.7  3355.5
#Mann= 4 ,-1,0
       0     .12       0   321.2    .045       0   336.8     .12       0
  347.34      .1       0
Bank Sta=321.2,336.8
XS Rating Curve= 0 ,0
Exp/Cntr(USF)=0,0
Exp/Cntr=0.3,0.1

Type RM Length L Ch R = 1 ,5313    ,249.4,253.5,256.8
XS GIS Cut Line= 2
2350481.73558227 723911.962080592350663.49572552723353.976506504
#Sta/Elev= 30
       0 3353.38    19.8 3351.22      45  3350.4    61.8 3346.32      66 3344.34
    70.2 3340.93    74.4 3339.43    82.9 3340.96    85.4 3340.43    87.1 3339.75
    91.3 3335.64    99.3 3323.26   102.5 3320.82   108.1 3317.92   120.7 3315.44
   133.3 3311.04   183.8 3304.53   242.7 3302.78   274.63293.908   284.8 3292.71
   293.2 3294.44   305.8 3301.03   314.2 3302.84   398.4 3303.48   415.2 3306.32
   434.1 3307.45   445.2 3307.04   485.7 3311.68   516.2 3312.06   586.8 3317.16
#Mann= 6 ,-1,0
       0      .1       0      90     .12       0   274.6    .045       0
   293.2     .12       0     400      .1       0     500     .12       0
Bank Sta=274.6,293.2
XS Rating Curve= 0 ,0
Exp/Cntr(USF)=0,0
Exp/Cntr=0.3,0.1

Type RM Length L Ch R = 1 ,5060    ,249.7,250,249.9
XS GIS Cut Line= 2
2350573.06003297724018.4517969982350964.88543742723564.058957671
#Sta/Elev= 30
       0 3349.32   121.1 3344.99   133.6 3342.68   145.6 3336.27   159.1 3335.21
   173.3 3332.63   197.1 3332.56   202.4 3331.04   207.7 3326.62   215.8 3317.89
   228.8  3301.4     230 3300.72     247 3296.75     262 3295.93   289.33292.552
   303.7 3291.55   310.1 3292.85   323.9  3297.2   384.5 3297.47   405.8 3300.73
     420 3301.43   445.6 3304.75     458 3307.47   464.2 3310.13   468.2 3313.26
   482.5 3328.39     507 3333.84   531.5 3335.34   581.7 3341.86     600 3346.35
#Mann= 7 ,-1,0
       0      .1       0     110     .12       0   289.3    .045       0
   310.1     .12       0     410      .1       0     510     .12       0
     560      .1       0
Bank Sta=289.3,310.1
XS Rating Curve= 0 ,0
Exp/Cntr(USF)=0,0
Exp/Cntr=0.3,0.1

Type RM Length L Ch R = 1 ,4810    ,231.7,237.9,241.9
XS GIS Cut Line= 2
2350737.62648424724188.5571867182351134.17825513723738.283166809
#Sta/Elev= 30
       0 3340.94    36.5 3338.17    47.1 3338.55    63.1    3335    94.6 3330.39
   100.7 3327.46   106.7 3322.07   151.6 3307.24   167.3 3304.98   185.4 3300.69
   201.7 3298.58   216.8 3297.92     223 3296.44   233.8 3291.52   239.9 3289.73
  284.78 3282.47   297.7 3281.59   310.23282.476   318.8  3284.9   330.1 3286.57
   385.1  3286.7   430.9 3290.54   457.6 3297.07   484.2  3307.7   505.5 3313.22
   521.5 3316.82   537.5 3319.12   545.5 3321.73   560.7 3322.74     600 3329.46
#Mann= 6 ,-1,0
       0     .12       0     150      .1       0     220     .12       0
  284.78    .045       0   310.2     .12       0     450      .1       0
Bank Sta=284.78,310.2
XS Rating Curve= 0 ,0
Exp/Cntr(USF)=0,0
Exp/Cntr=0.3,0.1

Type RM Length L Ch R = 1 ,4572    ,313.2,309.7,306.1
XS GIS Cut Line= 4
2350794.70520665724337.4620482452351021.19805845724178.050812162
2351071.28725622724155.2292024422351230.93574208723907.895745401
#Sta/Elev= 30
       0 3347.99      30  3342.9    44.3 3341.43    98.9 3340.53   167.8 3333.97
   173.5 3332.16   176.4 3329.47   182.8  3315.8   195.1 3301.46   199.3 3298.48
   212.1 3294.33   222.3 3287.83   246.4 3282.32   253.9 3283.56   288.9 3279.02
   298.4  3274.3   306.6 3272.54  313.42 3274.29   334.5 3281.18   348.7 3277.88
   405.9 3277.62   441.2 3279.58   487.5 3279.94   522.2 3283.07   548.7 3282.92
   571.4 3285.54   610.6 3300.52   614.8 3304.43   620.6 3313.23   626.4    3316
#Mann= 8 ,-1,0
       0      .1       0      30     .12       0      50      .1       0
  296.97     .12       0   298.4    .045       0  313.42     .12       0
  492.01      .1       0  602.01     .12       0
Bank Sta=298.4,313.42
XS Rating Curve= 0 ,0
Exp/Cntr(USF)=0,0
Exp/Cntr=0.3,0.1

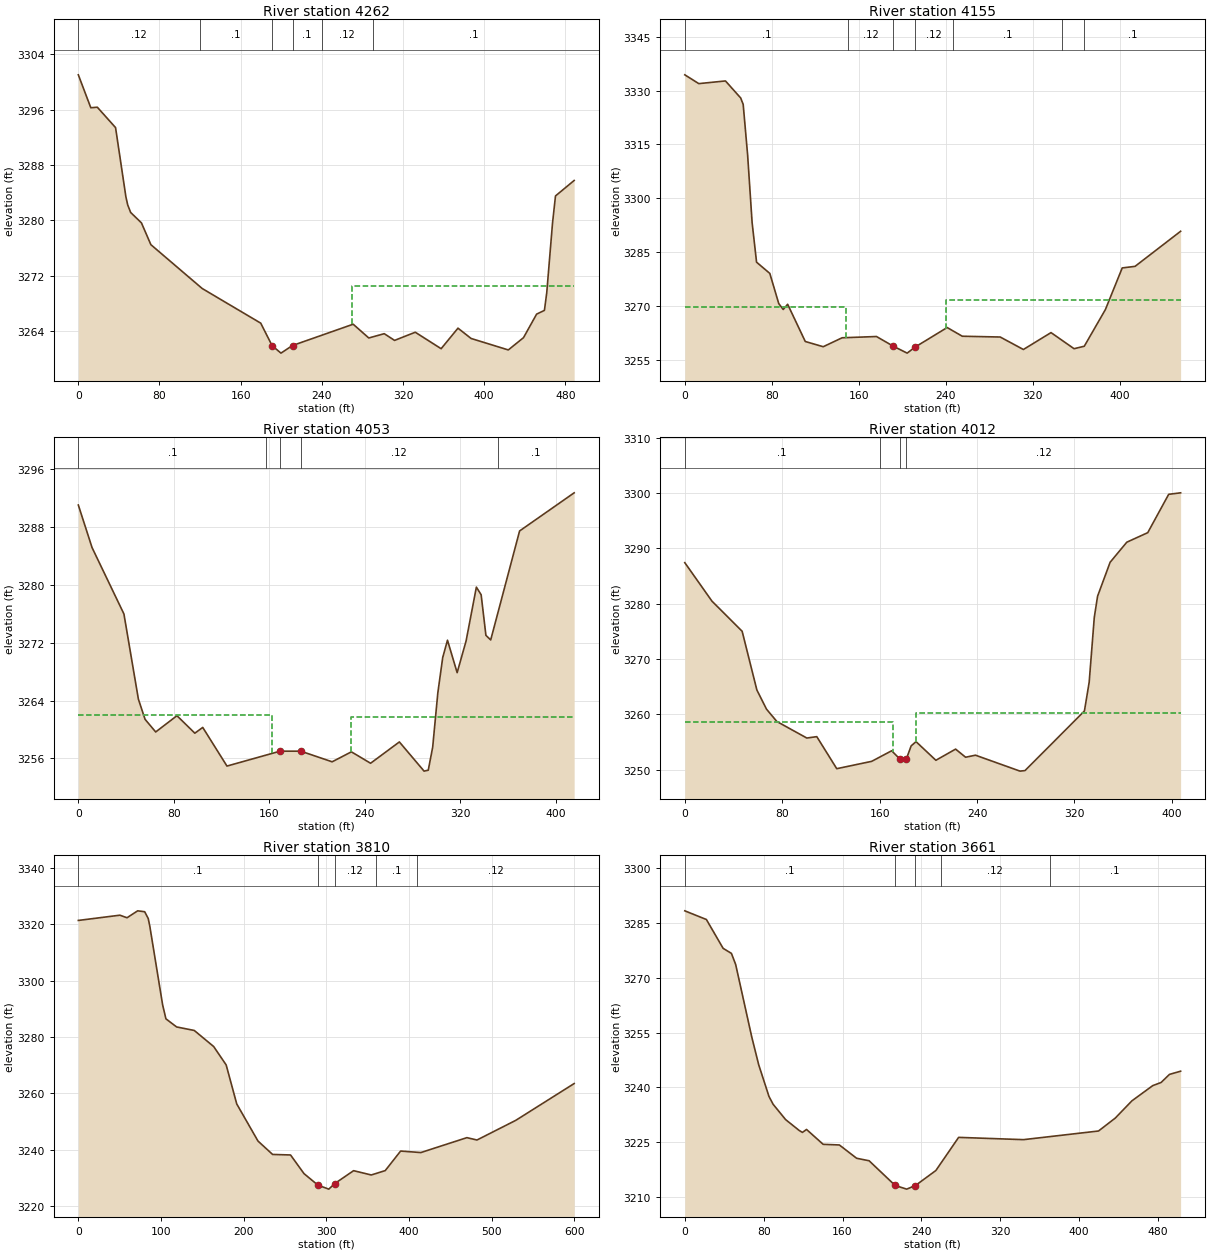
Type RM Length L Ch R = 1 ,4262    ,112,107.3,96
XS GIS Cut Line= 2
2351152.58786176724510.0309826382351455.02537722724126.200873036
#Sta/Elev= 30
       0 3301.04    12.3 3296.28    18.7 3296.36    36.7 3293.41    46.9 3283.39
    48.7 3282.22    51.6 3281.14    62.2 3279.64    71.5 3276.49   122.1 3270.15
   179.8 3265.14  190.94  3261.9   199.7 3260.81   211.1 3261.91   270.9 3264.99
   286.3    3263   301.5 3263.62   311.7 3262.65   332.1 3263.83   357.6 3261.45
   374.2 3264.42   387.1 3262.93   423.8 3261.27   438.8 3263.05   451.7 3266.45
   459.4 3266.99   461.7 3269.56   467.4 3279.64   470.3 3283.53   488.7 3285.77
#Mann= 6 ,-1,0
       0     .12       0     120      .1       0  190.94    .045       0
   211.1      .1       0     240     .12       0     290      .1       0
#XS Ineff= 2 , 0
                          270.14         3270.55
Permanent Ineff=
       F       F
Bank Sta=190.94,211.1
XS Rating Curve= 0 ,0
Exp/Cntr(USF)=0,0
Exp/Cntr=0.3,0.1

Type RM Length L Ch R = 1 ,4155    ,95,101.6,107
XS GIS Cut Line= 4
2351341.71342667724561.7822589292351377.91301835 724387.59789822
 2351371.0041683724328.8405433442351483.84365995724141.267984873
#Sta/Elev= 30
       0 3334.37    12.9 3331.92    37.4 3332.67    51.4 3327.93    53.7 3326.15
    57.8 3312.02    61.9 3293.29      66 3282.25    78.2 3279.12    86.4 3270.74
    90.5 3269.09    94.6 3270.54   110.8 3260.19   127.3 3258.73   144.7 3261.22
   176.3 3261.57   191.73258.882   204.5 3256.95   211.7 3258.61   241.3 3264.07
   255.2 3261.65   290.1 3261.43   311.4 3257.96   336.8 3262.66     358 3258.18
   367.4 3258.87   386.8 3269.06   402.3 3280.65   414.1 3281.09     456 3290.85
#Mann= 7 ,-1,0
       0      .1       0     150     .12       0   191.7    .045       0
   211.7     .12       0  247.07      .1       0  347.07     .12       0
  367.07      .1       0
#XS Ineff= 2 , 0
          148.08 3269.86  239.78         3271.64
Permanent Ineff=
       F       F
Bank Sta=191.7,211.7
XS Rating Curve= 0 ,0
Exp/Cntr(USF)=0,0
Exp/Cntr=0.3,0.1

Type RM Length L Ch R = 1 ,4053    ,46.8,41.6,38
XS GIS Cut Line= 5
2351433.26715202724559.5575497332351475.67007421724471.659521132
2351463.62049698724405.6134353012351476.36999591724382.323555989
2351502.01511914724159.813049651
#Sta/Elev= 30
       0 3291.08    11.5 3285.19    38.2    3276    50.3 3264.22    55.9 3261.42
    64.8 3259.67    82.6 3261.92    97.6  3259.5   104.2  3260.3   124.5 3254.95
     1693257.013  186.39 3257.01   212.6 3255.54   228.7 3256.92   244.8 3255.34
   268.9 3258.29   289.6 3254.25   293.1 3254.38   296.8 3257.56   301.1 3265.07
   305.2 3269.97   309.2 3272.37   317.3 3267.88   324.8 3272.28   333.4 3279.72
   337.4 3278.66   341.4 3273.04   345.4 3272.41   369.6 3287.49   415.3 3292.77
#Mann= 5 ,-1,0
       0      .1       0  157.59     .12       0     169    .045       0
  186.39     .12       0  351.28      .1       0
#XS Ineff= 2 , 0
          162.36 3262.02  228.44         3261.77
Permanent Ineff=
       F       F
Bank Sta=169,186.39
XS Rating Curve= 0 ,0
Exp/Cntr(USF)=0,0
Exp/Cntr=0.3,0.1

Type RM Length L Ch R = 1 ,4012    ,199.1,202.2,205.4
XS GIS Cut Line= 4
2351473.72640316724570.9691822592351511.08929735724405.071381634
2351511.02039504724383.1784287352351549.87178679724171.428977927
#Sta/Elev= 30
       0 3287.42    22.3 3280.47    47.1 3275.02    59.2 3264.41    67.1 3260.95
    75.6 3258.72   100.2 3255.73   108.4 3255.98   124.8 3250.19   153.5 3251.52
   169.9 3253.43  176.743251.911   181.9 3251.91   185.9 3254.31   189.9 3255.08
   206.2 3251.71   222.4 3253.73   230.6 3252.26   238.7 3252.63   275.3 3249.75
   279.4 3249.85   328.2 3260.62   332.1 3265.82   336.3 3277.53     339 3281.36
   349.3 3287.49     363 3291.12   380.2 3292.84   397.4 3299.77   407.2 3300.04
#Mann= 4 ,-1,0
       0      .1       0     160     .12       0  176.74    .045       0
   181.9     .12       0
#XS Ineff= 2 , 0
          170.58 3258.58  190.23         3260.22
Permanent Ineff=
       F       F
Bank Sta=176.74,181.9
XS Rating Curve= 0 ,0
Exp/Cntr(USF)=0,0
Exp/Cntr=0.3,0.1

Type RM Length L Ch R = 1 ,3810    ,148.4,148.4,147.9
XS GIS Cut Line= 2
2351595.43045185724700.1891242512351810.30291948724139.983963032
#Sta/Elev= 30
       0 3321.39    50.3 3323.25    58.9 3322.34    71.8  3324.8    80.3 3324.48
    84.6 3322.06    86.5 3319.34     102 3291.44     106 3286.47   118.9 3283.59
   140.3 3282.34   163.8 3276.63   178.9 3270.11   191.7 3256.26   217.4 3243.09
   235.1 3238.34   256.8 3238.15   273.1 3231.53   290.13227.409   303.1 3226.03
   310.33228.001   333.1 3232.58   354.5 3231.05   371.4 3232.61     390 3239.54
   414.5 3239.01   470.2  3244.3   482.4 3243.46   529.3 3250.43     600  3263.5
#Mann= 5 ,-1,0
       0      .1       0   290.1    .045       0   310.3     .12       0
     360      .1       0     410     .12       0
Bank Sta=290.1,310.3
XS Rating Curve= 0 ,0
Exp/Cntr(USF)=0,0
Exp/Cntr=0.3,0.1

Type RM Length L Ch R = 1 ,3661    ,149.8,151,150.1
XS GIS Cut Line= 2
2351773.47897158724665.9080786912351937.70961677724190.433872056
#Sta/Elev= 30
       0 3288.24    21.9 3285.87    38.9 3277.99    47.3 3276.62    51.6  3273.6
    67.9 3253.83      75 3246.19    85.4 3237.56    89.6 3235.42   102.3 3231.23
   115.9  3228.3   119.3 3227.74   123.5 3228.54   140.4 3224.48   156.8 3224.31
   174.3 3220.68     187 3219.99   213.4 3213.25   225.1 3212.25   233.93213.218
   254.7 3217.33   277.8 3226.38   343.6 3225.76   419.7 3228.12   436.7 3231.65
   453.6 3236.36   474.7 3240.51   483.2 3241.37   491.7 3243.58     503 3244.45
#Mann= 5 ,-1,0
       0      .1       0   213.4    .045       0   233.9      .1       0
     260     .12       0     370      .1       0
Bank Sta=213.4,233.9
XS Rating Curve= 0 ,0
Exp/Cntr(USF)=0,0
Exp/Cntr=0.3,0.1

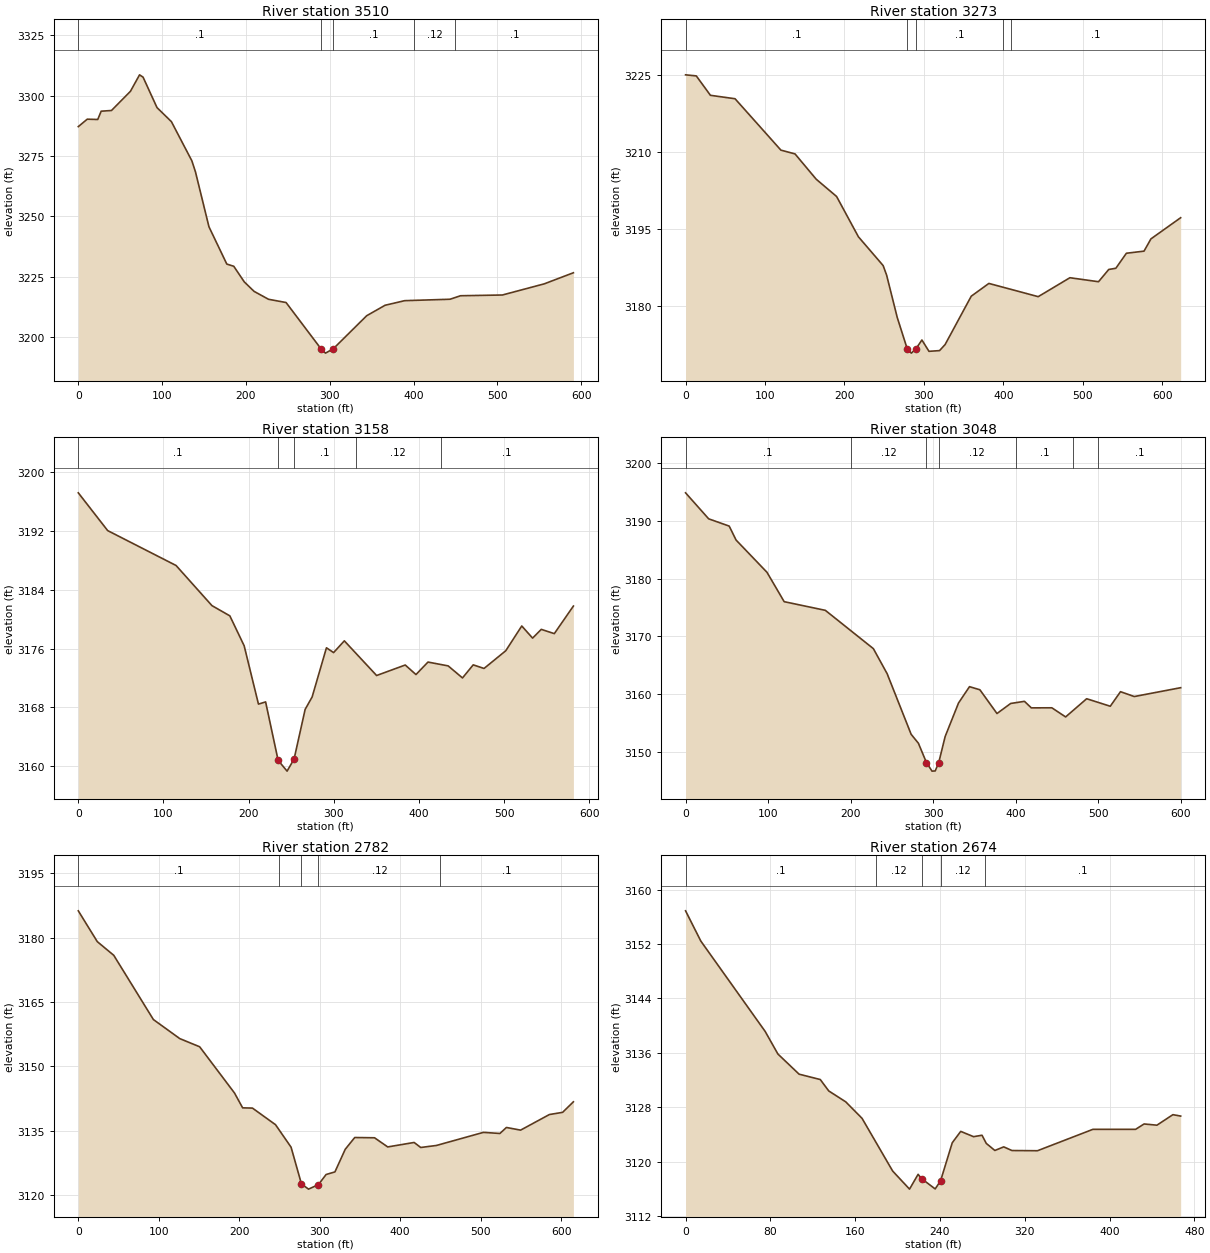
Type RM Length L Ch R = 1 ,3510    ,235.4,237.1,237.8
XS GIS Cut Line= 2
2351893.44535986724803.4362039472352056.82087104724235.775529512
#Sta/Elev= 30
       0 3287.17    10.7 3290.25    23.2 3290.12    27.3 3293.56    39.6 3293.85
    62.2  3301.8    73.1 3308.64    77.3 3307.66    93.9 3295.06   111.1 3289.22
   135.5 3272.99   139.8 3268.39   155.9 3245.63   177.2 3230.17   185.5 3229.26
     198 3222.81   209.7 3218.86     227 3215.57   247.9 3214.23   289.6 3195.03
   294.9 3193.25  304.143195.028   344.1 3208.76     366 3213.09   389.4    3215
   443.5 3215.59     456 3217.04     506 3217.35   555.9 3221.97   590.7 3226.57
#Mann= 5 ,-1,0
       0      .1       0   289.6    .045       0  304.14      .1       0
     400     .12       0     450      .1       0
Bank Sta=289.6,304.14
XS Rating Curve= 0 ,0
Exp/Cntr(USF)=0,0
Exp/Cntr=0.3,0.1

Type RM Length L Ch R = 1 ,3273    ,117.4,115.1,113.6
XS GIS Cut Line= 2
2352042.75665108724885.3576210372352312.54097161 724323.60346319
#Sta/Elev= 30
       0 3225.08    13.5 3224.87    31.3 3221.09    62.3 3220.42     120 3210.41
   137.8 3209.67   164.4 3204.75   190.1 3201.38   217.6 3193.52   248.7 3187.92
   253.1 3186.05   266.4 3177.83   279.1 3171.66   284.2 3170.86  290.073171.719
   297.5 3173.42   306.4 3171.21   319.7 3171.35   326.7 3172.53   359.6 3181.95
   381.8 3184.44   443.9 3181.86   483.8 3185.55   519.8 3184.77   532.7 3187.16
   541.6 3187.39   554.9 3190.32   577.1 3190.73   585.8 3193.12   623.2 3197.24
#Mann= 5 ,-1,0
       0      .1       0   279.1    .045       0  290.07      .1       0
     400     .12       0     410      .1       0
Bank Sta=279.1,290.07
XS Rating Curve= 0 ,0
Exp/Cntr(USF)=0,0
Exp/Cntr=0.3,0.1

Type RM Length L Ch R = 1 ,3158    ,111.3,109.8,109.8
XS GIS Cut Line= 3
2352180.29275591724925.8165007882352214.62225851724826.046383836
2352360.52264459724373.326068204
#Sta/Elev= 30
       0 3197.19    34.5 3192.05   114.8  3187.3   156.9 3181.84   177.9 3180.45
   194.7 3176.38   211.5 3168.44   219.9 3168.74   234.6 3160.78   245.1 3159.32
   253.3 3160.96   266.3 3167.72   274.5 3169.41   291.3  3176.1   299.7 3175.45
   312.3 3177.05   350.2 3172.33   383.8 3173.76   396.4 3172.46   410.5 3174.16
   434.2 3173.64     451    3172   463.6 3173.78   476.3 3173.29   501.8  3175.7
   520.6 3179.07   533.3 3177.42   543.5 3178.61   558.8 3178.03   581.2 3181.78
#Mann= 5 ,-1,0
       0      .1       0   234.6    .045       0   253.3      .1       0
  325.51     .12       0  425.51      .1       0
Bank Sta=234.6,253.3
XS Rating Curve= 0 ,0
Exp/Cntr(USF)=0,0
Exp/Cntr=0.3,0.1

Type RM Length L Ch R = 1 ,3048    ,264.8,265.9,264.1
XS GIS Cut Line= 2
2352282.17521605725000.0648187512352446.89179101724423.117290864
#Sta/Elev= 30
       0 3194.84      28 3190.34    52.9 3189.08    61.2 3186.67    98.7 3181.08
   119.5    3176   169.4  3174.5   227.6 3167.87   244.3 3163.53   273.4 3153.04
   282.2 3151.49  291.923148.153   298.7 3146.67   302.5  3146.7   306.7 3148.08
   314.6 3152.66   330.8 3158.46   344.1 3161.29   356.7 3160.75   377.4 3156.64
     394 3158.38   410.7 3158.75     419 3157.62   443.9 3157.63   460.6 3156.05
   486.1  3159.2   514.7  3157.9   527.1 3160.42   543.8 3159.58     600 3161.11
#Mann= 7 ,-1,0
       0      .1       0     200     .12       0  291.92    .045       0
   306.7     .12       0     400      .1       0     470     .12       0
     500      .1       0
Bank Sta=291.92,306.7
XS Rating Curve= 0 ,0
Exp/Cntr(USF)=0,0
Exp/Cntr=0.3,0.1

Type RM Length L Ch R = 1 ,2782    ,111.7,108.1,108.3
XS GIS Cut Line= 2
2352531.08829133 725056.228755722352666.63350585724456.095565248
#Sta/Elev= 30
       0 3186.23    23.6 3179.06    44.1 3175.87    93.3 3160.93   126.1 3156.49
   150.8 3154.59   194.1 3143.83   204.2 3140.38   216.4 3140.32   245.1 3136.45
   264.4 3131.22   277.3 3122.66   286.1 3121.46   298.4 3122.51   307.9 3124.86
   318.9 3125.47   331.7 3130.73   343.5 3133.47   368.1 3133.41   384.5 3131.28
   417.3 3132.32   425.5 3131.15     445 3131.62   503.4 3134.67   523.9 3134.41
     532 3135.81   549.6 3135.19   585.4 3138.82   601.8 3139.33   615.2 3141.78
#Mann= 5 ,-1,0
       0      .1       0     250     .12       0   277.3    .045       0
   298.4     .12       0     450      .1       0
Bank Sta=277.3,298.4
XS Rating Curve= 0 ,0
Exp/Cntr(USF)=0,0
Exp/Cntr=0.3,0.1

Type RM Length L Ch R = 1 ,2674    ,140.8,138.7,135.5
XS GIS Cut Line= 3
2352701.31812366724988.2119194592352694.98336491724805.911639925
2352725.95329657724522.959082502
#Sta/Elev= 30
       0  3156.9    14.4 3152.45    75.1 3139.15    87.1 3135.83   107.1 3132.86
   127.1 3132.07   135.1 3130.39   151.1 3128.79   166.5 3126.36   195.4  3118.6
   211.3 3115.94   219.4 3118.12   222.6 3117.49   235.5 3115.97   240.6 3117.16
   251.6 3122.76   259.6 3124.44   271.7 3123.66   279.7 3123.87   283.7 3122.67
   291.8 3121.63   300.2 3122.16   307.9 3121.62     332 3121.59   384.3 3124.74
   424.6 3124.74   432.6 3125.53   444.7 3125.35   459.8  3126.9   467.1 3126.69
#Mann= 5 ,-1,0
       0      .1       0     180     .12       0   222.6    .045       0
   240.6     .12       0  282.41      .1       0
Bank Sta=222.6,240.6
XS Rating Curve= 0 ,0
Exp/Cntr(USF)=0,0
Exp/Cntr=0.3,0.1

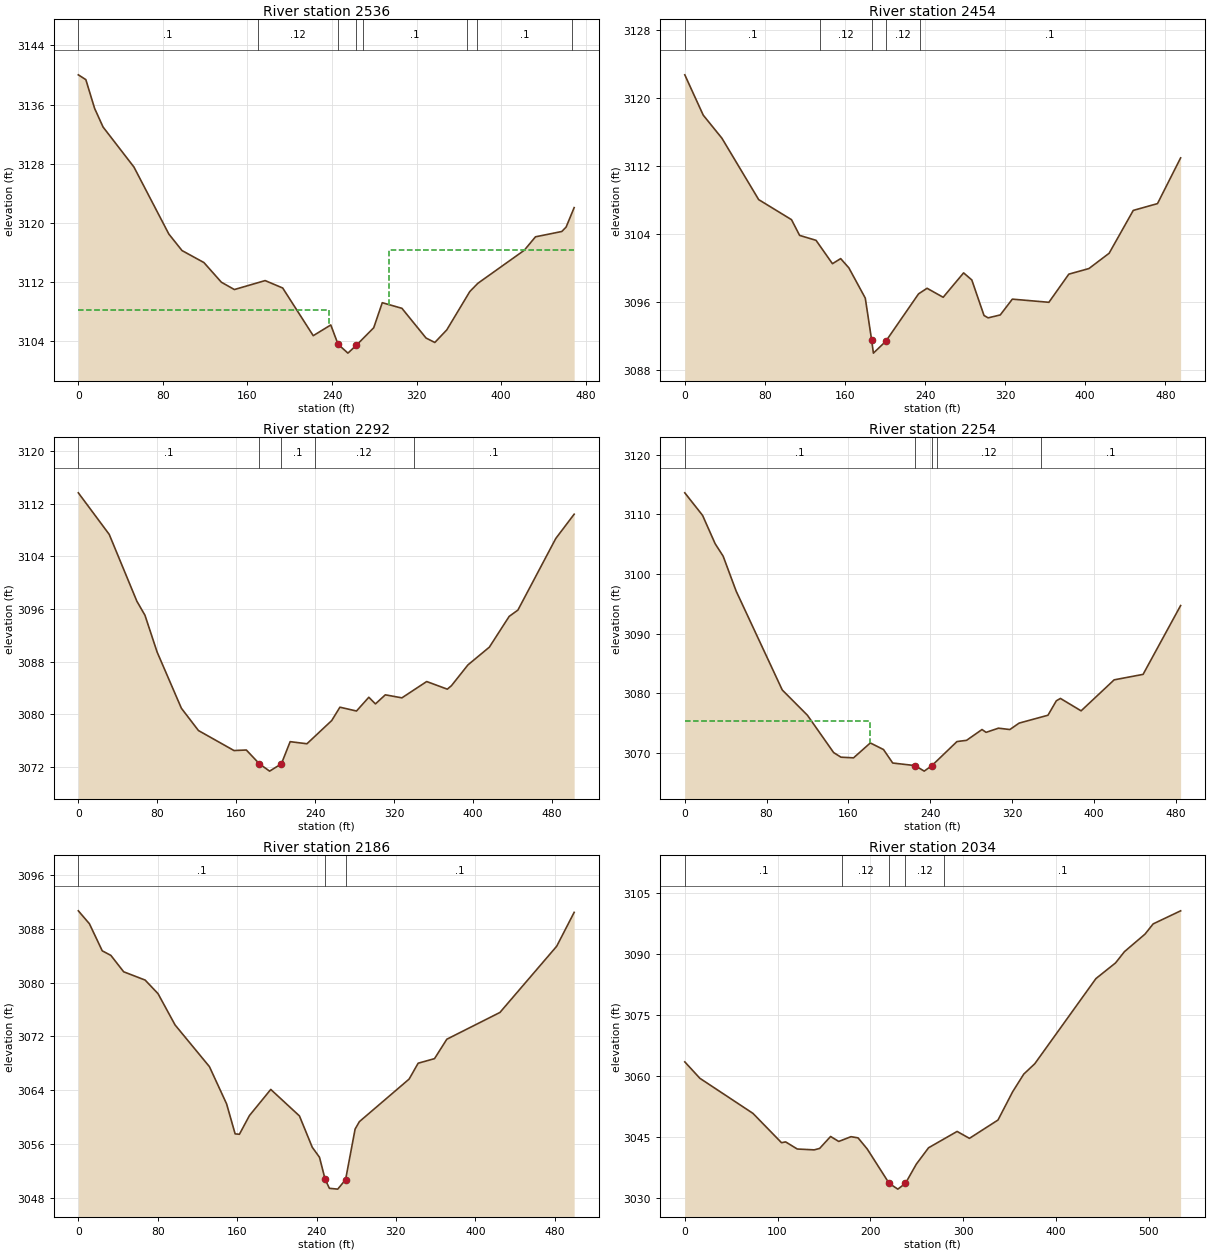
Type RM Length L Ch R = 1 ,2536    ,79.5,81.5,86.6
XS GIS Cut Line= 4
2352774.41837789724972.0589753082352835.31974787724740.988340996
2352826.95386904724693.2718469392352779.96979981724517.829881885
#Sta/Elev= 30
       0 3140.03     7.1 3139.38    15.4 3135.49    23.4 3132.97    52.6 3127.56
    85.6  3118.5    98.1 3116.26   118.8 3114.64   135.3 3111.98   147.6 3110.99
   176.7  3112.2   193.3  3111.2   222.2 3104.75   238.8  3106.2  245.64  3103.6
     255 3102.39   263.1 3103.47   279.4 3105.82   287.5 3109.21   306.1 3108.45
   328.9 3104.43   337.2 3103.83   348.5 3105.53   370.3 3110.72   377.9 3111.83
   421.8  3116.3   432.4 3118.12   457.3 3118.84   461.4 3119.44     469 3122.07
#Mann= 8 ,-1,0
       0      .1       0     170     .12       0  245.64    .045       0
   263.1     .12       0  268.96      .1       0  367.41     .12       0
  377.41      .1       0  467.41     .12       0
#XS Ineff= 2 , 0
          237.39 3108.19  293.68         3116.39
Permanent Ineff=
       F       F
Bank Sta=245.64,263.1
XS Rating Curve= 0 ,0
Exp/Cntr(USF)=0,0
Exp/Cntr=0.3,0.1

Type RM Length L Ch R = 1 ,2454    ,160.6,162.2,151.2
XS GIS Cut Line= 4
2352888.60433433724945.8488841232352879.91467898724891.779917516
2352932.05261106724653.297154092 2352908.8801968724458.262667405
#Sta/Elev= 30
       0 3122.73    18.4 3117.99    37.1 3115.27    73.8 3108.05   106.6 3105.69
   114.7 3103.84   131.1 3103.26   147.5 3100.51   155.7 3101.11   163.9 3100.02
   180.3 3096.46  186.613091.551   188.4 3089.99   200.7 3091.37   233.5 3096.96
     242 3097.62   258.1 3096.56   278.5 3099.43   286.7  3098.6   298.9 3094.42
     303 3094.14   315.1 3094.48   327.2 3096.34   363.7 3095.97   383.6 3099.28
   403.7 3099.94   423.9 3101.74     448 3106.78   472.2 3107.58   495.3 3112.96
#Mann= 5 ,-1,0
       0      .1       0  134.76     .12       0  186.61    .045       0
   200.7     .12       0  234.76      .1       0
Bank Sta=186.61,200.7
XS Rating Curve= 0 ,0
Exp/Cntr(USF)=0,0
Exp/Cntr=0.3,0.1

Type RM Length L Ch R = 1 ,2292    ,40.8,38.2,38.4
XS GIS Cut Line= 4
 2353024.6547771724939.0225831152353061.15140258724776.321440613
2353038.30781283724728.6478620182352955.94392579 724458.17809929
#Sta/Elev= 30
       0 3113.66    31.3 3107.34    59.3 3097.18    67.5 3095.05    79.8 3089.46
   104.4 3080.91   121.7 3077.52   157.7 3074.48   170.2 3074.56  183.533072.444
   193.8 3071.35   205.7 3072.46   214.6 3075.83   231.6 3075.51   256.7 3079.04
     265 3081.07   281.8 3080.49   294.3 3082.58     301 3081.57     311 3082.95
   327.8 3082.49   352.9 3084.97   373.8 3083.81     378 3084.34   394.7  3087.5
   416.4  3090.2   436.5 3094.88   445.3 3095.83   483.7 3106.72   502.3 3110.41
#Mann= 5 ,-1,0
       0      .1       0  183.53    .045       0   205.7      .1       0
  239.61     .12       0  339.61      .1       0
Bank Sta=183.53,205.7
XS Rating Curve= 0 ,0
Exp/Cntr(USF)=0,0
Exp/Cntr=0.3,0.1

Type RM Length L Ch R = 1 ,2254    ,67.1,67.6,68.1
XS GIS Cut Line= 4
2353056.37170536724946.1675833572353097.13010034724764.210571474
2353060.10276154724691.1575166012353030.06267879724476.823511637
#Sta/Elev= 30
       0 3113.63    17.4 3109.84    29.7 3105.08    37.5    3103    50.2 3097.14
    95.3 3080.54   119.9  3076.3   145.5 3070.04   152.7 3069.26     165 3069.15
   181.4 3071.65   194.3 3070.54   203.3 3068.28   225.1 3067.85   234.1 3066.92
   241.7 3067.86   266.1 3071.88   275.5 3072.09   290.6  3073.9   294.6 3073.43
   306.7 3074.13   317.8  3073.9   326.9 3074.98   355.1  3076.3   363.3 3078.73
   367.3 3079.12   387.5 3077.04   419.8 3082.24   448.1 3083.16   484.8 3094.71
#Mann= 5 ,-1,0
       0      .1       0   225.1    .045       0   241.7      .1       0
  246.47     .12       0  348.37      .1       0
#XS Ineff= 2 , 0
          180.92 3075.25
Permanent Ineff=
       F       F
Bank Sta=225.1,241.7
XS Rating Curve= 0 ,0
Exp/Cntr(USF)=0,0
Exp/Cntr=0.3,0.1

Type RM Length L Ch R = 1 ,2186    ,152.2,152.5,152
XS GIS Cut Line= 3
2353234.47635497724935.5428487232353115.39589281724642.669279607
2353071.41121759724464.584984833
#Sta/Elev= 30
       0 3090.69    11.2 3088.76    24.1 3084.74    32.8 3084.06    45.7 3081.62
    67.3 3080.39    80.3 3078.37    97.5 3073.71   132.1 3067.51   149.4 3061.97
     158 3057.51   162.3 3057.45   172.4 3060.23   193.9 3064.12   222.8 3060.18
   235.7 3055.52     243 3054.03   248.7 3050.73     253 3049.41   261.4 3049.29
   269.3 3050.71   278.9 3058.23   283.2 3059.33   333.3 3065.66   342.4 3068.02
   358.9  3068.7   371.3 3071.59   424.8 3075.57     482 3085.42   499.6 3090.46
#Mann= 3 ,-1,0
       0      .1       0   248.7    .045       0   269.3      .1       0
Bank Sta=248.7,269.3
XS Rating Curve= 0 ,0
Exp/Cntr(USF)=0,0
Exp/Cntr=0.3,0.1

Type RM Length L Ch R = 1 ,2034    ,58.2,58.2,59.7
XS GIS Cut Line= 2
2353378.23114714724867.9566404662353154.85869706724382.303834587
#Sta/Elev= 30
       0 3063.51    16.3 3059.47    73.5 3050.85   104.3 3043.64   108.7 3043.84
   121.3 3042.09   139.5 3041.88   145.4 3042.24   157.2 3045.17     166 3043.95
   179.2 3045.12   186.8 3044.83   196.7  3042.1  220.373033.642   229.7 3032.23
   237.9 3033.65   249.6 3038.36   262.8 3042.39   293.6 3046.41   306.9 3044.71
   337.7 3049.22   353.5 3056.17   365.5 3060.51   377.3 3063.04   443.3 3083.99
   464.4 3087.83   474.1 3090.62   496.2 3094.91     505 3097.43   534.6 3100.64
#Mann= 5 ,-1,0
       0      .1       0     170     .12       0  220.37    .045       0
   237.9     .12       0     280      .1       0
Bank Sta=220.37,237.9
XS Rating Curve= 0 ,0
Exp/Cntr(USF)=0,0
Exp/Cntr=0.3,0.1

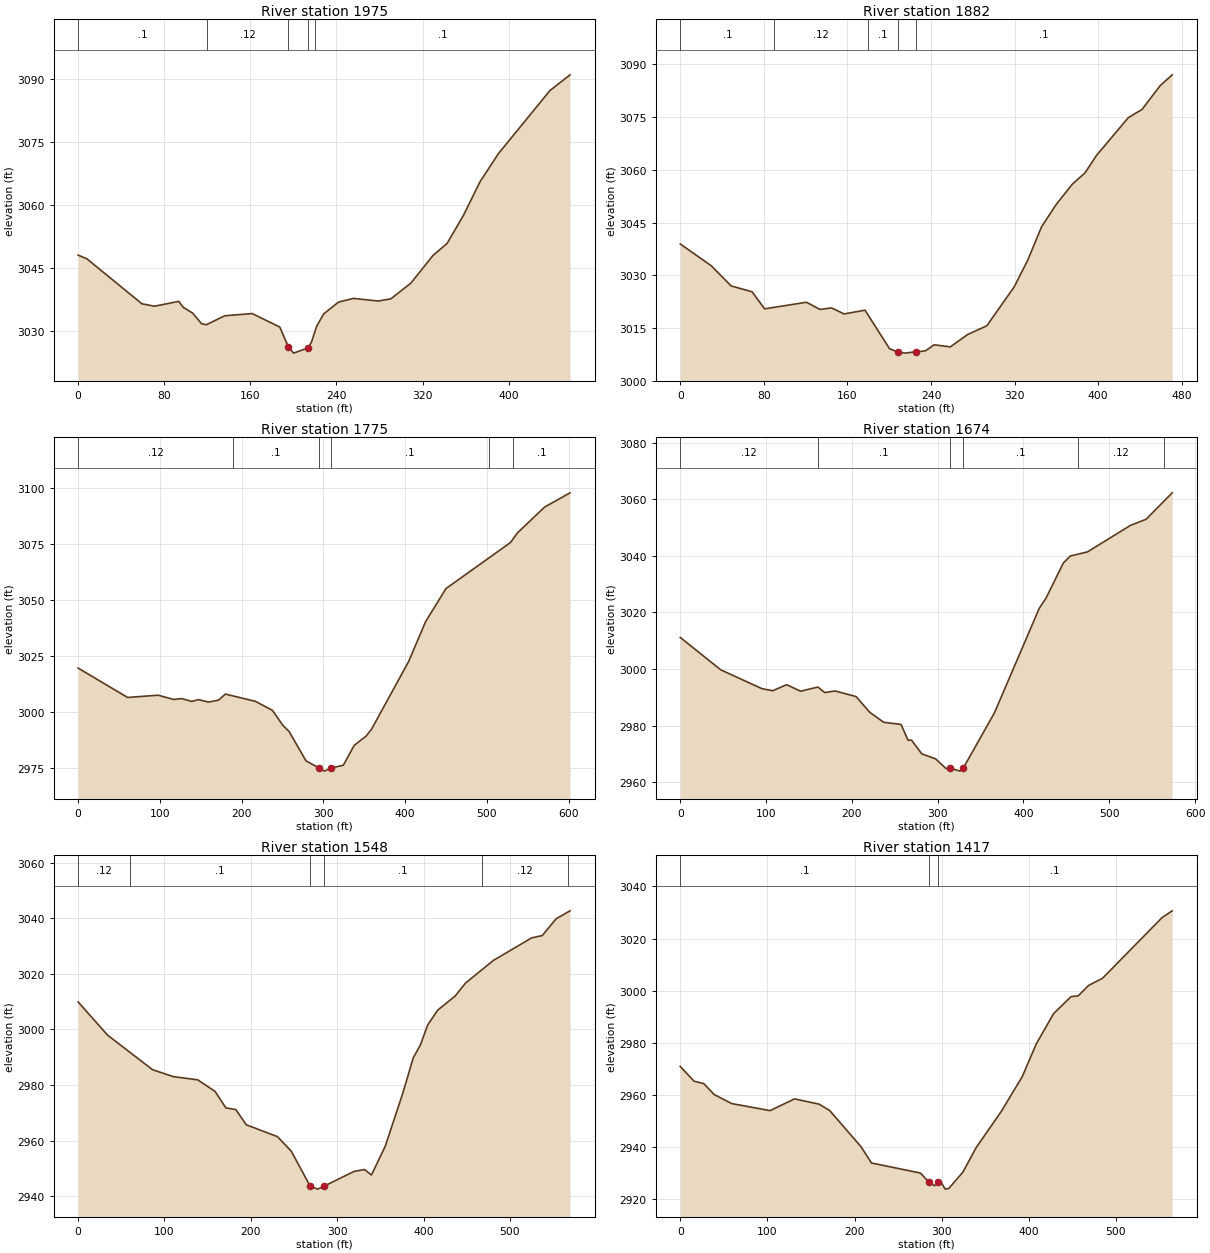
Type RM Length L Ch R = 1 ,1975    ,98.4,93.8,85.1
XS GIS Cut Line= 3
 2353403.9782741724820.7535743812353317.08172062724587.956634827
2353235.54915193724395.925979618
#Sta/Elev= 30
       0 3047.98     8.1 3047.11    59.3 3036.38      71  3035.8    93.5 3036.96
    97.7 3035.53   106.3 3034.18   114.8 3031.61   119.1 3031.39   136.2 3033.52
   161.8 3034.05   187.4 3030.83   195.4 3026.09   200.2 3024.62     214  3025.9
   217.2 3027.51   221.6 3031.01   228.2 3033.98     242 3036.78   255.8 3037.67
   278.8 3037.04   290.6 3037.56   309.3 3041.33   329.7 3047.89   342.8 3050.75
   358.1 3057.48   373.6 3065.54   390.6 3072.19   438.4 3087.21   457.1 3090.96
#Mann= 5 ,-1,0
       0      .1       0     120     .12       0   195.4    .045       0
     214     .12       0     220      .1       0
Bank Sta=195.4,214
XS Rating Curve= 0 ,0
Exp/Cntr(USF)=0,0
Exp/Cntr=0.3,0.1

Type RM Length L Ch R = 1 ,1882    ,101,106.4,110.2
XS GIS Cut Line= 4
2353423.80632803724797.9117428012353419.55813394724589.003155426
2353388.38095898724575.2740167572353296.87909483724366.695465594
#Sta/Elev= 30
       0 3038.93    29.7 3032.73    48.7    3027    68.7 3025.34    80.7 3020.49
   120.8 3022.36   133.7 3020.32   144.8 3020.75   156.8 3019.04   176.8 3020.11
   200.3 3009.13   208.2 3008.23   214.4 3007.89  225.443008.257   234.5 3008.52
     243 3010.26   258.4 3009.66   275.1  3013.2   293.4 3015.67   319.6 3026.74
   332.7 3034.43   345.8 3043.84   360.1 3050.31   375.3 3055.97   387.5 3059.21
   398.2 3064.06   428.8 3074.87   441.9  3077.2   459.3 3083.97   470.8 3087.05
#Mann= 5 ,-1,0
       0      .1       0      90     .12       0     180      .1       0
   208.2    .045       0  225.44      .1       0
Bank Sta=208.2,225.44
XS Rating Curve= 0 ,0
Exp/Cntr(USF)=0,0
Exp/Cntr=0.3,0.1

Type RM Length L Ch R = 1 ,1775    ,99.7,100.8,106.5
XS GIS Cut Line= 4
2353537.76963468724796.3945625782353471.63477498724518.681097387
 2353447.9175085724478.4746837392353373.41419112724219.344055109
#Sta/Elev= 30
       0 3019.46    60.5 3006.33    97.9 3007.34   116.9 3005.42   126.7 3005.82
     139 3004.55   147.2 3005.37   159.6 3004.27   171.9 3005.15   180.1 3007.85
     190 3006.97   217.1 3004.57   237.7 3000.56     250  2994.1   258.2 2991.06
   278.8    2978  294.212974.917   301.2 2973.41   309.6 2974.83   324.4 2976.02
   337.7  2984.9   352.4  2989.1   358.9 2992.11   404.3 3022.37   425.1 3040.21
     450 3054.98   529.1 3075.61   537.4 3079.85   570.7 3091.41   601.8 3097.77
#Mann= 6 ,-1,0
       0     .12       0     190      .1       0  294.21    .045       0
   309.6      .1       0  502.16     .12       0  532.16      .1       0
Bank Sta=294.21,309.6
XS Rating Curve= 0 ,0
Exp/Cntr(USF)=0,0
Exp/Cntr=0.3,0.1

Type RM Length L Ch R = 1 ,1674    ,125.3,126.2,132.8
XS GIS Cut Line= 3
2353597.92107668724775.9514387622353555.40816574 724475.09083826
2353529.24637439724206.932476942
#Sta/Elev= 30
       0 3011.18    47.2 2999.73    95.3 2993.06   107.8 2992.35     124 2994.49
   140.2 2992.17   160.3 2993.65   168.4 2991.71   180.5 2992.26   204.8 2990.29
   220.9 2984.71   237.1 2981.19   257.3 2980.44   265.4 2974.86   269.5 2974.88
   281.5 2970.03   297.6 2968.27   309.8  2964.8   313.8 2965.08   325.9 2963.93
  329.912965.055   366.1 2984.51   418.3 3021.44   426.3  3025.1   446.4 3037.47
   454.5 3039.96   474.6 3041.43   524.6 3050.78   542.9 3052.96   573.3  3062.3
#Mann= 6 ,-1,0
       0     .12       0     160      .1       0   313.8    .045       0
  329.91      .1       0  463.85     .12       0  563.85      .1       0
Bank Sta=313.8,329.91
XS Rating Curve= 0 ,0
Exp/Cntr(USF)=0,0
Exp/Cntr=0.3,0.1

Type RM Length L Ch R = 1 ,1548    ,132.3,131.1,124.3
XS GIS Cut Line= 4
 2353632.9509287 724775.198011582353654.63661743724525.002068207
2353674.14552553 724482.924031122353637.07391474724213.230143229
#Sta/Elev= 30
       0 3009.93    34.1 2997.97    86.3  2985.5   110.4 2983.02   138.5 2981.87
   158.6  2977.7   171.1 2971.77   182.7 2971.15   194.7 2965.69   230.9  2961.4
   246.9 2956.15   268.6 2943.66   277.4 2942.51   285.3 2943.65   319.5 2948.88
   331.6 2949.58   339.7  2947.6   355.8 2958.04     376 2977.05   388.1  2989.8
   396.2  2994.3   404.9 3001.66   416.4 3006.97   436.6 3012.05   448.7 3016.74
     481 3024.89   525.4 3033.02   537.5 3033.82   553.6 3039.88   569.7 3042.74
#Mann= 6 ,-1,0
       0     .12       0      60      .1       0   268.6    .045       0
   285.3      .1       0  467.51     .12       0  567.51      .1       0
Bank Sta=268.6,285.3
XS Rating Curve= 0 ,0
Exp/Cntr(USF)=0,0
Exp/Cntr=0.3,0.1

Type RM Length L Ch R = 1 ,1417    ,124.2,121.2,118.8
XS GIS Cut Line= 4
2353800.38508476724768.0017576942353778.71613012724494.671851435
2353786.45541299724450.5414725172353767.68284557724205.523243711
#Sta/Elev= 30
       0 2970.96    15.9 2965.28    26.9  2964.4    38.9 2960.19      59 2956.72
   103.1 2954.02   131.2 2958.52   159.3  2956.5   171.4  2954.1   207.5 2940.18
   219.5 2933.94   275.7 2930.09  285.46 2926.58   291.9 2925.23     296 2926.52
   300.1 2926.17   304.1 2923.92   308.2 2924.17   324.4 2930.43   339.7 2939.86
   368.5 2953.71   392.6 2967.07   408.6 2979.56   428.7 2991.28   448.7 2997.75
   456.8 2998.02   468.8 3002.03   484.8 3004.78     553    3028   564.7 3030.62
#Mann= 3 ,-1,0
       0      .1       0  285.46    .045       0     296      .1       0
Bank Sta=285.46,296
XS Rating Curve= 0 ,0
Exp/Cntr(USF)=0,0
Exp/Cntr=0.3,0.1