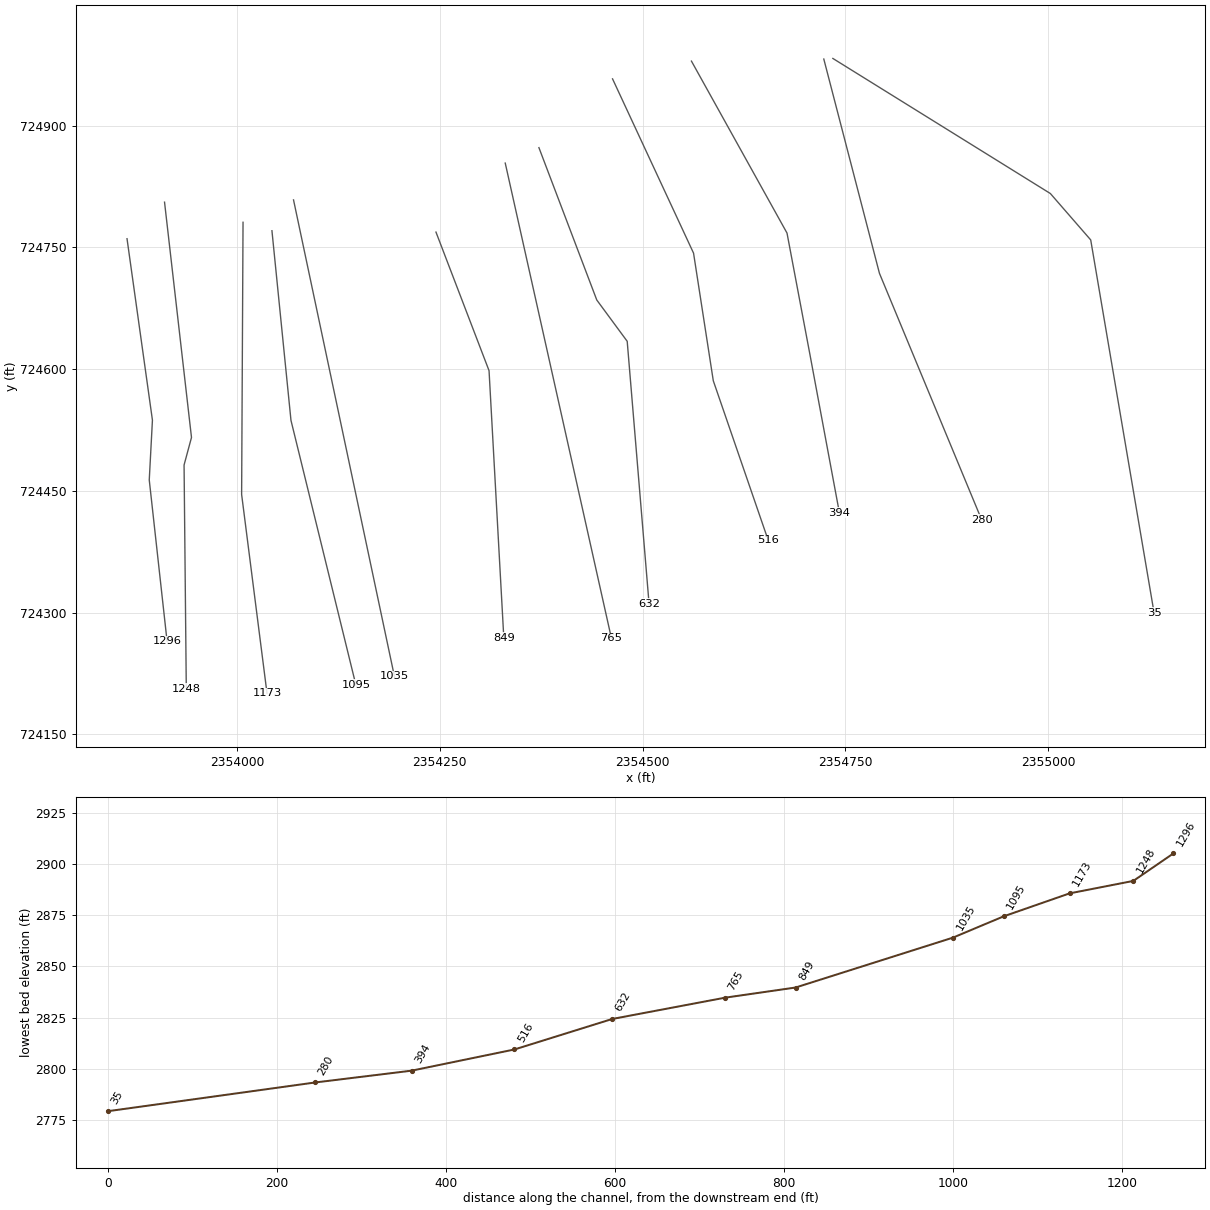
HEC-RAS study OTTERCKT1.prj: OTTERCKT1

--- OTTERCKT1.g01 (geometry) --- (continued)

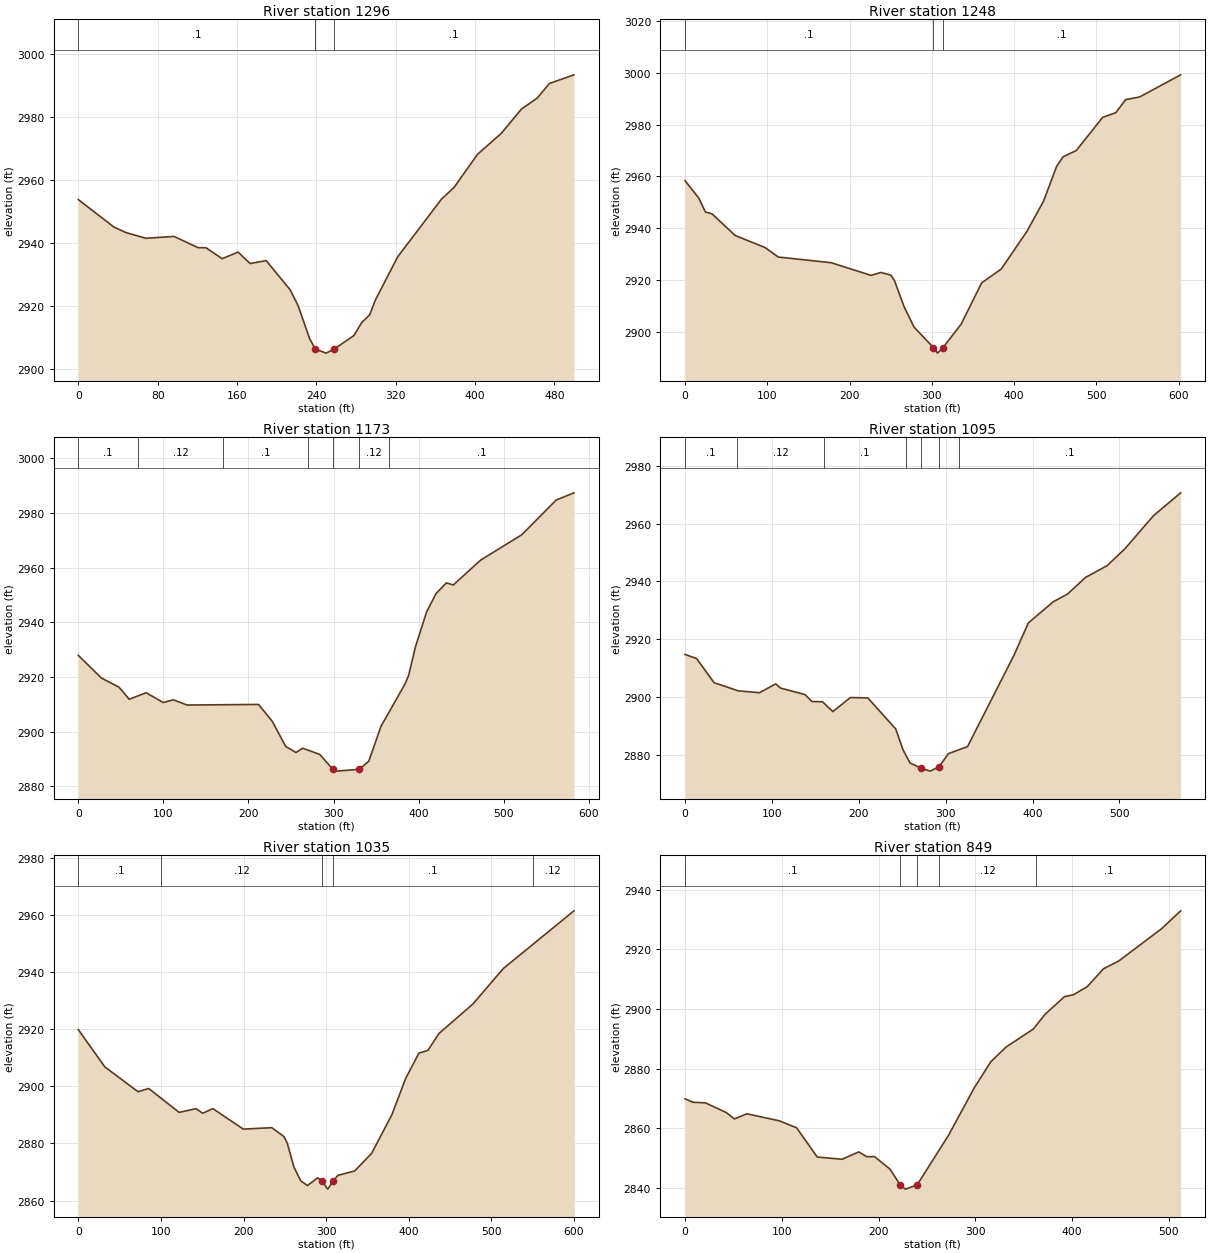
Type RM Length L Ch R = 1 ,1296    ,50.2,47.5,45.8
XS GIS Cut Line= 4
2353864.60545997724760.739215118 2353895.9265612724537.080016561
  2353892.013059724463.4029692362353913.97457483 724264.56978603
#Sta/Elev= 30
       0 2953.78    35.9 2945.07      48 2943.33    68.2 2941.52    96.5 2942.11
   120.7 2938.55   128.8 2938.51     145 2935.05   161.1 2937.15   173.2 2933.52
   189.4 2934.44   213.6 2925.19   221.7 2920.11   233.1 2909.79  238.932906.424
   249.8 2905.13   257.8 2906.38   277.8 2910.69   285.8 2914.84   293.8  2917.3
   299.6 2922.03     322 2935.65   366.2 2953.94   378.9 2957.67   402.5 2968.13
   426.6 2974.81   446.7 2982.44   462.8 2985.97   474.9 2990.56   499.7 2993.31
#Mann= 3 ,-1,0
       0      .1       0  238.93    .045       0   257.8      .1       0
Bank Sta=238.93,257.8
XS Rating Curve= 0 ,0
Exp/Cntr(USF)=0,0
Exp/Cntr=0.3,0.1

Type RM Length L Ch R = 1 ,1248    ,69.5,75.4,82.4
XS GIS Cut Line= 4
2353910.84298855724805.7704906232353944.06257372724515.775078523
2353934.91448522 724481.825505652353937.65214369724206.369732197
#Sta/Elev= 30
       0 2958.39    16.7 2951.65    24.8 2946.24    32.8 2945.56      61 2937.15
    97.2 2932.54   113.3 2928.84   177.7 2926.65   226.1 2921.75   238.1 2922.89
   250.2 2921.85   254.6 2919.74   266.3 2909.68   278.4 2901.77  302.032893.822
     307  2891.7   313.5 2893.79   335.7 2902.91   360.6 2918.85   384.4  2924.2
   415.7 2938.79   435.9 2950.48   451.7 2963.86   459.6 2967.58   475.7 2970.03
   507.7 2982.83   523.7 2984.65   535.7 2989.69   552.7 2990.72   602.5 2999.27
#Mann= 3 ,-1,0
       0      .1       0  302.03    .045       0   313.5      .1       0
Bank Sta=302.03,313.5
XS Rating Curve= 0 ,0
Exp/Cntr(USF)=0,0
Exp/Cntr=0.3,0.1

Type RM Length L Ch R = 1 ,1173    ,73.9,78,82.5
XS GIS Cut Line= 3
2354007.58633634724780.9856687012354005.84840527 724445.56497229
2354037.13116452724200.516691492
#Sta/Elev= 30
       0 2927.95    27.1 2919.67    47.8 2916.31    59.8 2911.91    79.8 2914.28
    99.8 2910.69   111.8  2911.7   127.8 2909.79   211.8    2910   227.8 2903.89
   243.8 2894.63   255.8 2892.45   263.8 2893.99   283.8 2891.73  299.142886.281
   303.8 2885.62   330.1 2886.29   341.4 2889.24   355.7 2901.99   384.2 2917.62
   388.2 2920.64   396.3 2931.17   409.4 2943.87   420.5 2950.55   432.6 2954.47
   440.7 2953.68   472.9 2962.79   521.3 2972.07   561.6 2984.74   582.5 2987.38
#Mann= 7 ,-1,0
       0      .1       0      70     .12       0     170      .1       0
     270     .12       0  299.14    .045       0   330.1     .12       0
  365.43      .1       0
Bank Sta=299.14,330.1
XS Rating Curve= 0 ,0
Exp/Cntr(USF)=0,0
Exp/Cntr=0.3,0.1

Type RM Length L Ch R = 1 ,1095    ,58.7,60,59.4
XS GIS Cut Line= 3
2354043.21392326724770.558082285 2354066.6759927724536.806353438
 2354146.6208219724210.944277909
#Sta/Elev= 30
       0 2914.78    13.4 2913.33    33.5 2904.99    61.7 2902.14    85.8 2901.54
   104.4 2904.58   109.9 2903.14   138.1 2900.89   146.1 2898.48   158.2  2898.4
   170.2    2895   190.3 2899.85   210.4 2899.74   242.5 2889.03     251 2881.75
     259 2877.24   271.2 2875.51   282.2 2874.41   292.4 2875.92   303.3 2880.48
   325.2 2882.88   378.7  2914.5   395.2 2925.66     424    2933   440.5 2935.69
   461.1 2941.41   485.8 2945.45   506.4 2951.31   539.3 2962.76   570.5 2970.65
#Mann= 7 ,-1,0
       0      .1       0      60     .12       0     160      .1       0
  254.93     .12       0   271.2    .045       0   292.4     .12       0
  314.93      .1       0
Bank Sta=271.2,292.4
XS Rating Curve= 0 ,0
Exp/Cntr(USF)=0,0
Exp/Cntr=0.3,0.1

Type RM Length L Ch R = 1 ,1035    ,187.3,186.2,184.5
XS GIS Cut Line= 2
2354069.81698007724808.5529159372354194.11271988724221.568615409
#Sta/Elev= 30
       0 2919.86    32.1  2906.8    72.3 2898.11    85.2 2899.25     122 2890.89
   142.5 2892.17   150.6 2890.57   162.9  2892.2   199.7 2885.03   234.3 2885.52
   248.8 2882.44   252.9 2880.17     261 2871.77   269.2 2866.95   277.4 2865.27
   289.7 2867.98     295 2866.83   301.9 2864.02   308.5 2866.83   314.2 2868.84
   334.6 2870.38   355.1 2876.55   379.6 2890.05   396.2 2902.71   412.3 2911.63
   423.2 2912.58   436.7 2918.53   477.7 2928.82   514.5 2941.23     600 2961.43
#Mann= 5 ,-1,0
       0      .1       0     100     .12       0     295    .045       0
   308.5      .1       0     550     .12       0
Bank Sta=295,308.5
XS Rating Curve= 0 ,0
Exp/Cntr(USF)=0,0
Exp/Cntr=0.3,0.1

Type RM Length L Ch R = 1 ,849     ,82,83.6,85.2
XS GIS Cut Line= 3
2354245.37428745724768.8628020192354310.77876582724598.084441831
2354328.94667648724269.245258914
#Sta/Elev= 30
       0 2869.92     8.2 2868.78    21.1 2868.58    42.5 2865.36    51.1 2863.18
    63.9 2864.91    97.3 2862.58   115.3 2860.23   136.7 2850.42   162.4 2849.68
   179.6 2852.14   187.8 2850.54   195.8 2850.57   211.8 2846.39  222.282841.141
   227.8 2839.67   239.9 2841.08   272.4 2857.76   298.9 2873.59     316 2882.34
     332 2887.33     360 2893.32   372.1 2898.26   392.1 2904.14   401.5 2904.82
   415.6 2907.49   432.5 2913.51   448.2  2916.1   492.3 2926.87   512.2 2932.92
#Mann= 5 ,-1,0
       0      .1       0  222.28    .045       0   239.9      .1       0
  262.87     .12       0  362.87      .1       0
Bank Sta=222.28,239.9
XS Rating Curve= 0 ,0
Exp/Cntr(USF)=0,0
Exp/Cntr=0.3,0.1

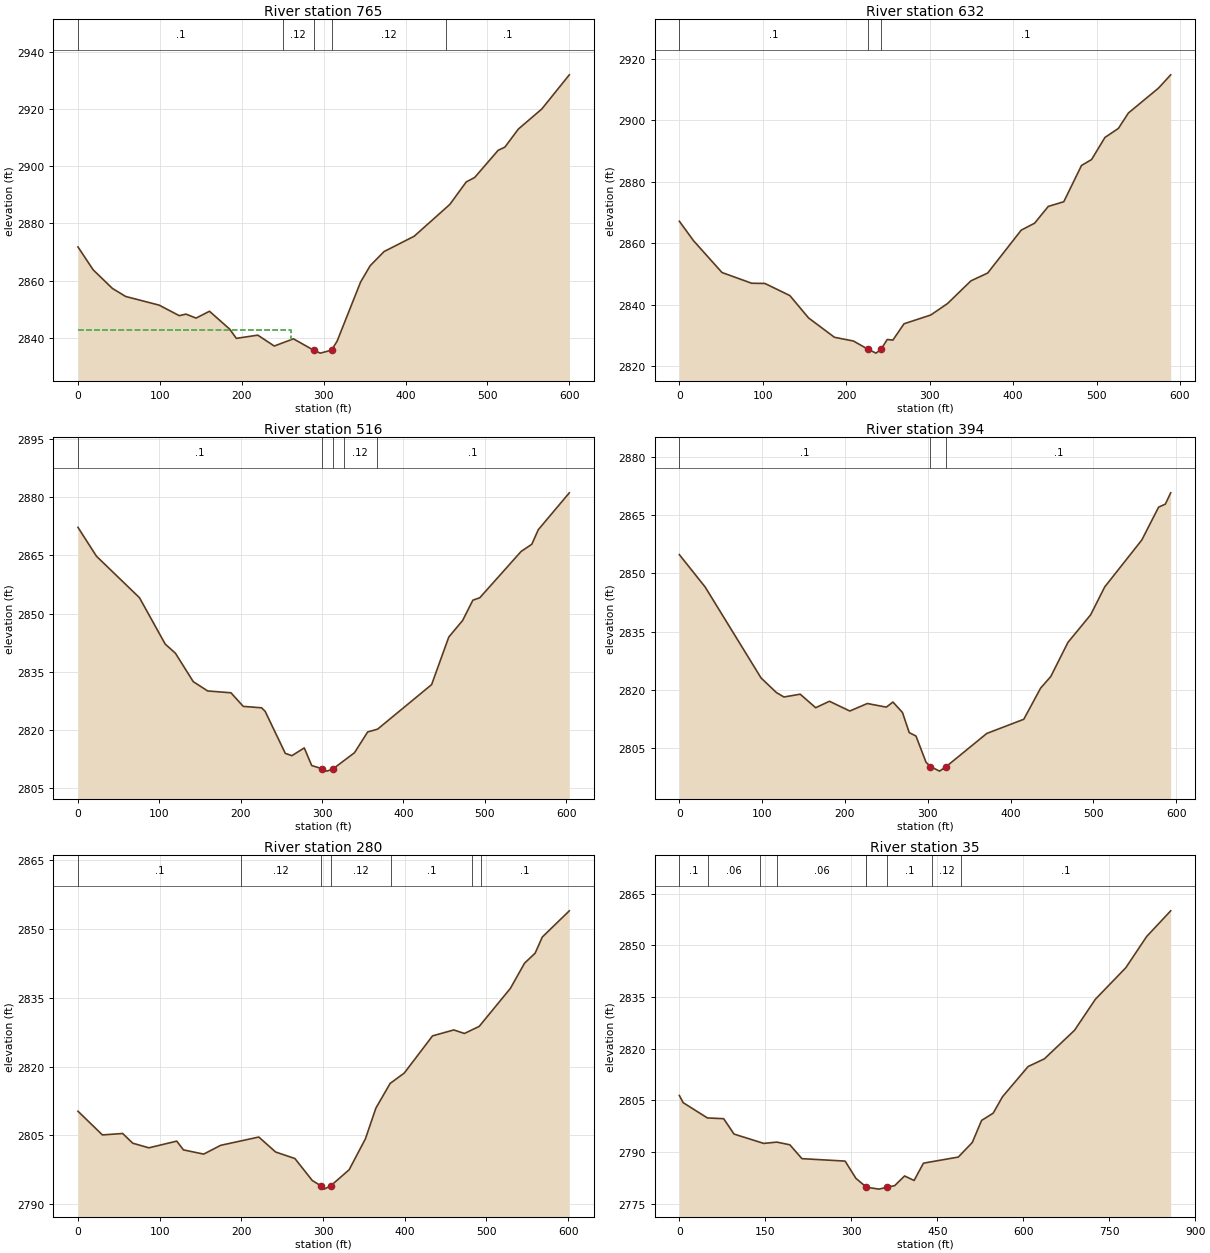
Type RM Length L Ch R = 1 ,765     ,124.2,133.4,136.2
XS GIS Cut Line= 2
2354330.73303392 724853.933483092354461.58344144724268.375483527
#Sta/Elev= 30
       0  2871.8    18.6 2863.79      42 2857.32    58.2  2854.5    99.1 2851.47
   123.7 2847.79   131.9 2848.33   144.2 2846.94   160.6 2849.33   185.2  2843.1
   193.4 2839.86   219.6 2840.98   239.7 2837.18   263.1  2839.7   287.7 2835.73
   295.9  2834.7   309.62835.734   316.4 2838.85   345.1 2859.53   356.9 2865.27
   373.8 2870.19   410.6 2875.55   454.1 2886.66   474.1 2894.51   484.4 2896.06
   513.1 2905.57   521.3 2906.67   537.8 2912.99   566.4    2920     600 2931.94
#Mann= 5 ,-1,0
       0      .1       0     250     .12       0   287.7    .045       0
   309.6     .12       0     450      .1       0
#XS Ineff= 2 , 0
          259.97 2842.72
Permanent Ineff=
       F       F
Bank Sta=287.7,309.6
XS Rating Curve= 0 ,0
Exp/Cntr(USF)=0,0
Exp/Cntr=0.3,0.1

Type RM Length L Ch R = 1 ,632     ,118.4,115.7,110.6
XS GIS Cut Line= 4
2354372.24694525724872.9585825892354443.54805078724685.177522325
2354481.04335316724634.2899552892354508.00804888724310.648807485
#Sta/Elev= 30
       0  2867.2    16.9 2860.89    51.1 2850.52    86.6 2847.04   102.5 2846.97
   132.4 2843.03   154.8 2835.76   185.8 2829.47   208.7 2828.24   225.7 2825.62
   235.6 2824.31  241.672825.555   249.1 2828.74   255.9 2828.55   269.2 2833.85
   301.3 2836.71   321.4 2840.44   349.4 2847.81   369.5 2850.36   409.7 2864.31
   425.7 2866.56   442.1 2872.02   460.7 2873.55   481.9 2885.33     494 2887.27
     510 2894.44   526.1 2897.38   538.1 2902.39   574.3 2910.52   588.8 2914.81
#Mann= 3 ,-1,0
       0      .1       0   225.7    .045       0  241.67      .1       0
Bank Sta=225.7,241.67
XS Rating Curve= 0 ,0
Exp/Cntr(USF)=0,0
Exp/Cntr=0.3,0.1

Type RM Length L Ch R = 1 ,516     ,121.6,121.7,121.8
XS GIS Cut Line= 4
2354462.98761296724957.7211128812354562.81698786724742.930795582
2354587.14802283724585.6480337932354654.77794589724389.199813199
#Sta/Elev= 30
       0 2872.21    22.7 2864.79    75.6 2854.09   107.2 2842.15   119.7 2839.81
   141.7 2832.47   159.4 2830.08     188 2829.61   203.1 2826.11   225.6 2825.74
     230 2824.84   254.8    2814   262.9 2813.41   278.1 2815.41   287.2 2810.88
   299.3 2810.09   306.2 2809.43   313.9 2810.08   339.8 2814.17     356 2819.52
   368.2 2820.24   434.6 2831.72   455.7 2843.97   472.7 2848.23   485.3 2853.46
   493.8 2854.09   544.6 2866.02   557.7 2867.86   565.7 2871.62   603.8 2881.11
#Mann= 5 ,-1,0
       0      .1       0   299.3    .045       0   313.9      .1       0
  326.86     .12       0  366.86      .1       0
Bank Sta=299.3,313.9
XS Rating Curve= 0 ,0
Exp/Cntr(USF)=0,0
Exp/Cntr=0.3,0.1

Type RM Length L Ch R = 1 ,394     ,115.3,114.3,115.5
XS GIS Cut Line= 4
 2354560.2219759724979.5946000632354677.98632233724767.693214529
2354705.69324319724620.958577513 2354742.5974585724422.812979652
#Sta/Elev= 30
       0 2854.82    31.2 2846.47    98.7 2823.06   117.2 2819.31   126.3 2818.17
   145.9 2818.89   164.6 2815.41   181.2 2817.07   205.8 2814.56     227 2816.49
   249.9 2815.56   257.9 2816.87   269.4 2814.18   277.6 2808.99   285.7 2808.13
   297.9 2801.35   303.1 2800.27   314.2 2799.08   322.3 2800.26   371.2 2808.78
   415.9 2812.43   436.3 2820.48   448.5 2823.44   469.2 2832.22   496.6 2839.32
   513.6  2846.5   558.4 2858.59   578.7 2867.05   586.8 2867.83   593.3 2870.74
#Mann= 3 ,-1,0
       0      .1       0   303.1    .045       0   322.3      .1       0
Bank Sta=303.1,322.3
XS Rating Curve= 0 ,0
Exp/Cntr(USF)=0,0
Exp/Cntr=0.3,0.1

Type RM Length L Ch R = 1 ,280     ,239,245.4,250.3
XS GIS Cut Line= 3
2354723.33716768724982.1546466722354791.92261076724718.050381801
2354917.78004845724414.535085596
#Sta/Elev= 30
       0 2810.28    29.9 2805.12    54.7 2805.43    67.1 2803.31    86.8 2802.31
   120.9 2803.77   129.1 2801.86   153.9 2800.94   174.6 2802.85   221.3 2804.66
     242 2801.39   265.5 2799.98   286.8 2795.19  297.072794.064   301.3 2793.31
   309.22794.008   331.9 2797.53   351.8 2804.26   364.7 2810.98   382.1 2816.34
   399.4  2818.6     434  2826.7     460 2827.99     473 2827.22   491.1 2828.76
   529.3 2837.05   546.6 2842.53   559.6 2844.72   568.3 2848.22   601.4 2853.94
#Mann= 7 ,-1,0
       0      .1       0     200     .12       0  297.07    .045       0
   309.2     .12       0  382.86      .1       0  482.86     .12       0
  492.86      .1       0
Bank Sta=297.07,309.2
XS Rating Curve= 0 ,0
Exp/Cntr(USF)=0,0
Exp/Cntr=0.3,0.1

Type RM Length L Ch R = 1 ,35      ,,,
XS GIS Cut Line= 4
2354734.49903355724982.8891380722355002.57650906724816.399691715
2355052.28813839724759.2343853852355130.36275013724299.812286616
#Sta/Elev= 30
       0 2806.43     6.7 2804.35    48.9 2799.93    77.3 2799.71    95.4 2795.25
   147.3 2792.54     170 2792.92   192.8 2792.14   213.9 2788.12   289.2 2787.41
     308 2782.42  326.342779.842   348.5 2779.28   362.2 2779.83   375.7 2780.29
     393  2783.1   409.6 2781.79   425.9 2786.81   486.7 2788.58   511.1 2792.81
   527.3  2799.2   547.6 2801.32   563.8 2806.07   608.5 2814.84   636.9 2817.07
   689.6 2825.37   725.9 2834.36   778.9 2843.48   815.4 2852.56   857.3    2860
#Mann= 9 ,-1,0
       0      .1       0      50     .06       0     140      .1       0
     170     .06       0  325.57      .1       0  326.34    .045       0
   362.2      .1       0  441.33     .12       0  491.33      .1       0
Bank Sta=326.34,362.2
XS Rating Curve= 0 ,0
Exp/Cntr(USF)=0,0
Exp/Cntr=0.3,0.1
LCMann Table=0

Chan Stop Cuts=-1
Use User Specified Reach Order=0
Composite Channel Slope=5